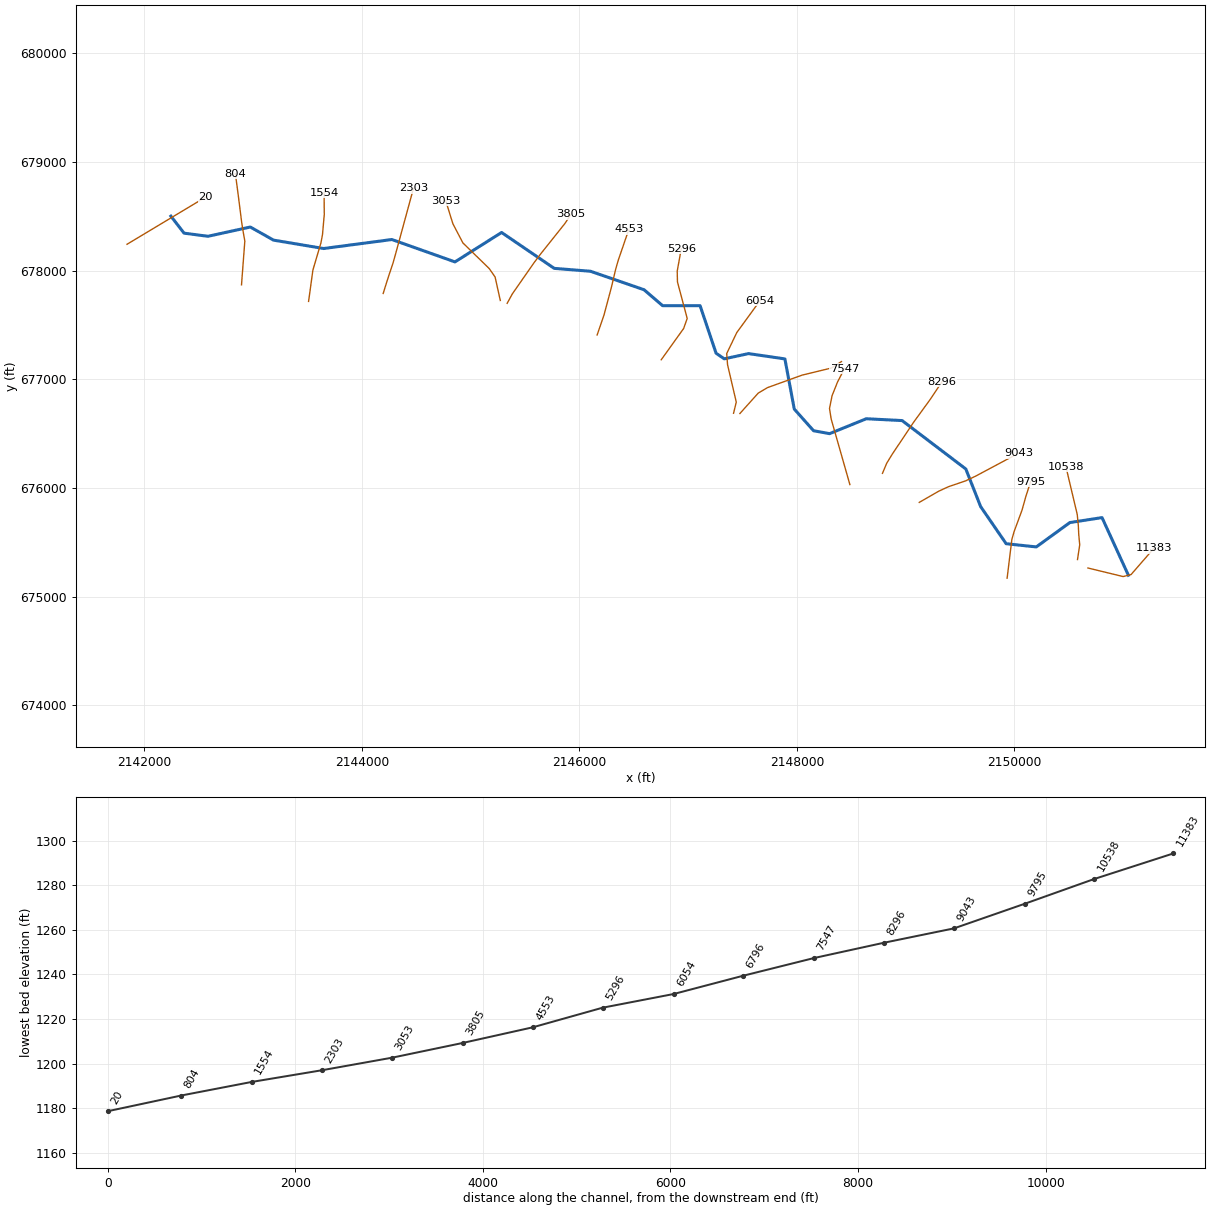
--- WFORKRV.prj (project) ---

Proj Title=WFORKRV
Current Plan=p01
Default Exp/Contr=0,0
English Units
Geom File=g01
Flow File=f01
Plan File=p01
BEGIN DESCRIPTION:
---------- MODELED AS PART OF WVEMD CTP PROGRAM, 2023----------
Stream Name: West Fork River
Flood Zone:  AFH
Upshur County, WV
HEC-RAS Version: RAS 6.3
Vertical Datum: NAVD88
Projection: NAD 1983 StatePlane West Virginia S FIPS 4702 (US Feet)
Terrain: 1-meter LIDAR (FEMA Region III 3DEP collected 2016-2018)
Land Use: 2019 NLCD
Hydrologic Method:
WV SIR2010-5033 regression equations
Additional Model Notes:
DS extent crosses county boundary into Lewis County
END DESCRIPTION:
DSS Export Rating Curves= 0
DSS Export Rating Curve Sorted= 0
DSS Export Volume Flow Curves= 0
DXF OffsetX= 0
DXF OffsetY= 0
DXF ScaleX= 0
DXF ScaleY= 0

--- WFORKRV.p01 (plan) ---

Plan Title=Floodplain
Program Version=6.30
Short Identifier=Floodplain
Geom File=g01
Flow File=f01
Subcritical Flow
K Sum by GR= 0
Std Step Tol= 0.01
Critical Tol= 0.01
Num of Std Step Trials= 20
Max Error Tol= 0.3
Flow Tol Ratio= 0.001
Split Flow NTrial= 30
Split Flow Tol= 0.02
Split Flow Ratio= 0.02
Log Output Level= 0
Friction Slope Method= 1
Unsteady Friction Slope Method= 2
Unsteady Bridges Friction Slope Method= 1
Parabolic Critical Depth
Global Vel Dist= 0 , 0 , 0
Global Log Level= 0
CheckData=True
Encroach Param=-1 ,0,0, 0
Mapping Interval=1HOUR
Computation Time Step Use Courant=        0
Computation Time Step Use Time Series=    0
Computation Time Step Count To Double=0
Computation Time Step Max Doubling=0
Computation Time Step Max Halving=0
Computation Time Step Residence Courant=0
Run HTab= 0
Run UNet= 0
Run Sediment= 0
Run PostProcess= 0
Run WQNet= 0
Run RASMapper= 0
UNET Theta= 0
UNET Theta Warmup= 0
UNET ZTol= 0
UNET ZSATol= 0
UNET MxIter= 0
UNET Max Iter WO Improvement= 0
UNET MaxInSteps= 0
UNET DtIC= 0
UNET DtMin= 0
UNET MaxCRTS= 0
UNET WFStab= 0
UNET SFStab= 0
UNET WFX= 1
UNET SFX= 1
UNET Gravity=32.17405
UNET 1D Methodology=Finite Difference
UNET DSS MLevel= 1
UNET Pardiso=0
UNET DZMax Abort= 0
UNET Use Existing IB Tables= 0
UNET Froude Reduction=False
UNET Froude Limit= 0
UNET Froude Power= 0
UNET D1 Cores= 0
UNET WindReference=Eulerian
UNET WindDragFormulation=Hsu (1988)
UNET D2 Coriolis=0
UNET D2 Cores= 0
UNET D2 Theta= 1
UNET D2 Theta Warmup= 1
UNET D2 Z Tol= 0.01
UNET D2 Volume Tol= 0.01
UNET D2 Max Iterations= 20
UNET D2 Equation= 0
UNET D2 RampUpFraction=0.1
UNET D2 TimeSlices= 1
UNET D2 Turbulence Formulation=Non-Conservative (original)
UNET D2 Eddy Viscosity=0.3
UNET D2 Transverse Eddy Viscosity=0.1
UNET D2 Smagorinsky Mixing=0
UNET D2 BCVolumeCheck=0
UNET D2 Cores=0
UNET D2 SolverType=PARDISO (Direct)
UNET D2 Minimum Iterations= 3
UNET D2 Maximum Iterations= 30
UNET D2 Restart Number= 10
UNET D2 Relaxation Coeff=1.3
UNET D2 SOR Precondition Iterations= 10
UNET D2 ILUT Maximum Fill= 8
UNET D2 ILUT Tolerance=1E-08
UNET D2 Convergence Tolerance=0.00001
UNET D1D2 MaxIter= 0
UNET D1D2 ZTol=0.01
UNET D1D2 QTol=0.1
UNET D1D2 MinQTol=1
Write IC File= 0
Write IC File at Fixed DateTime=0
Write IC File at Sim End=0
Echo Input=False
Echo Parameters=False
Echo Output=False
Write Detailed= 0
HDF Write Warmup=0
HDF Write Time Slices=0
HDF Flush=0
HDF Compression= 1
HDF Chunk Size= 1
HDF Spatial Parts= 1
HDF Use Max Rows=0
HDF Fixed Rows= 1
Calibration Method= 0
Calibration Iterations= 20
Calibration Max Change=0.05
Calibration Tolerance=0.2
Calibration Maximum=1.5
Calibration Minimum=0.5
Calibration Optimization Method= 1
WQ AD Non Conservative
WQ ULTIMATE=-1
WQ Max Comp Step=1HOUR
WQ Output Interval=15MIN
WQ Output Selected Increments= 0
WQ Output face flow=0
WQ Output face velocity=0
WQ Output face area=0
WQ Output face dispersion=0
WQ Output cell volume=0
WQ Output cell surface area=0
WQ Output cell continuity=0
WQ Output cumulative cell continuity=0
WQ Output face conc=0
WQ Output face dconc_dx=0
WQ Output face courant=0
WQ Output face peclet=0
WQ Output face adv mass=0
WQ Output face disp mass=0
WQ Output cell mass=0
WQ Output cell source sink temp=0
WQ Output nsm pathways=0
WQ Output nsm derived pathways=0
WQ Create Restart=0
WQ Fixed Restart=0
WQ System Summary=0
WQ Write To DSS=0
Sorting and Armoring Iterations= 10
XS Update Threshold= 0.02
Bed Roughness Predictor= 0
Hydraulics Update Threshold= 0.02
Energy Slope Method= 1
Volume Change Method= 1
Sediment Retention Method= 0
Sediment TS Multiplier= 1
Warm Up Method= 0
XS Weighting Method= 0
Number of US Weighted Cross Sections= 1
Number of DS Weighted Cross Sections= 1
Upstream XS Weight=0
Main XS Weight=1
Downstream XS Weight=0
Number of DS XS's Weighted with US Boundary= 1
Upstream Boundary Weight= 1
Weight of XSs Associated with US Boundary= 0
Number of US XS's Weighted with DS Boundary= 1
Downstream Boundary Weight= 0.5
Weight of XSs Associated with DS Boundary= 0.5
Percentile Method= 0
Sediment Output Level= 3
Mass or Volume Output= 0
Output Increment Type= 1
Profile and TS Output Increment= 1
Transport Output Increment 1
XS Output Flag= 0
XS Output Increment= 10
Read HDF5 Sediment Hotstart= 0
Sediment Hotstart Type= 0
Write Gradation File= 0
Read Gradation Hotstart= 0
Write HDF5 File= 1
Write Binary Output= 1
Write DSS Sediment File= 0
DSS Sediment Output Type= 1
SV Curve= 0
Specific Gage Flag= 0
Subcell Erosion Methods= 0
Subcell Deposition Methods= 0
Advection Scheme= 1
Matrix Solver= 0
Implicit Weighting Factor= 1
Maximum Outer Loop Convergence Iterations= 5
Convergence Maximum Absolute= 0.001
Convergence RMSE= 0.0001
Grain Fractions Max Abs Error= 0.001
Max Subgrid Regions= 1
Max Subgrid Length Scale= 3.402823E+38
Initial Layer Thickness= 3.402823E+38
Min Layer Thickness= 3.402823E+38
Max Layer Thickness= 3.402823E+38
Number of Layers= 5

--- WFORKRV.f01 (steady flow) ---

Flow Title=Flows
Program Version=6.30
Number of Profiles= 1
Profile Names=01pct
River Rch & RM=WFORKRV,Main,11383
    2060
River Rch & RM=WFORKRV,Main,5296
    2300
Boundary for River Rch & Prof#=WFORKRV,Main            , 1
Up Type= 0
Dn Type= 3
Dn Slope=0.002178
DSS Import GetInterval= 0
DSS Import GetPeak= 0
DSS Import FillOption= 0

--- WFORKRV.g01 (geometry) ---

Geom Title=Geometry
Program Version=6.30

River Reach=WFORKRV         ,Main
Reach XY= 30
2151047.59157684675198.0626396692150805.44600001675728.262000009
2150509.43800002675682.5610000192150200.95300004675458.409000009
2149923.83200002675487.9980000112149689.40700004675829.249000013
2149553.05000003 676175.564000012148967.32999998676621.063999996
2148638.01200001676637.9190000152148300.31000002676500.790000007
2148153.07900003676527.5460000192147975.77199999676726.773000017
2147889.46500003677188.3270000072147555.54000001677237.347000018
2147331.90300003677189.3569999932147256.81400001 677240.49500002
2147109.78300002677678.1250000152146765.24100001677678.039000019
2146594.17384948677825.0002011212146101.88500004677994.966000006
2145768.33200003678021.665000007     2145284.601678351.726000011
2144855.72700001678081.1299999952144275.70100002678286.996000007
2143648.48699999678204.2370000182143187.47700001678281.530000001
2142974.05600002      678401.9192142584.24400002      678316.728
2142364.81300002678345.6589999942142243.92594111 678502.08171615

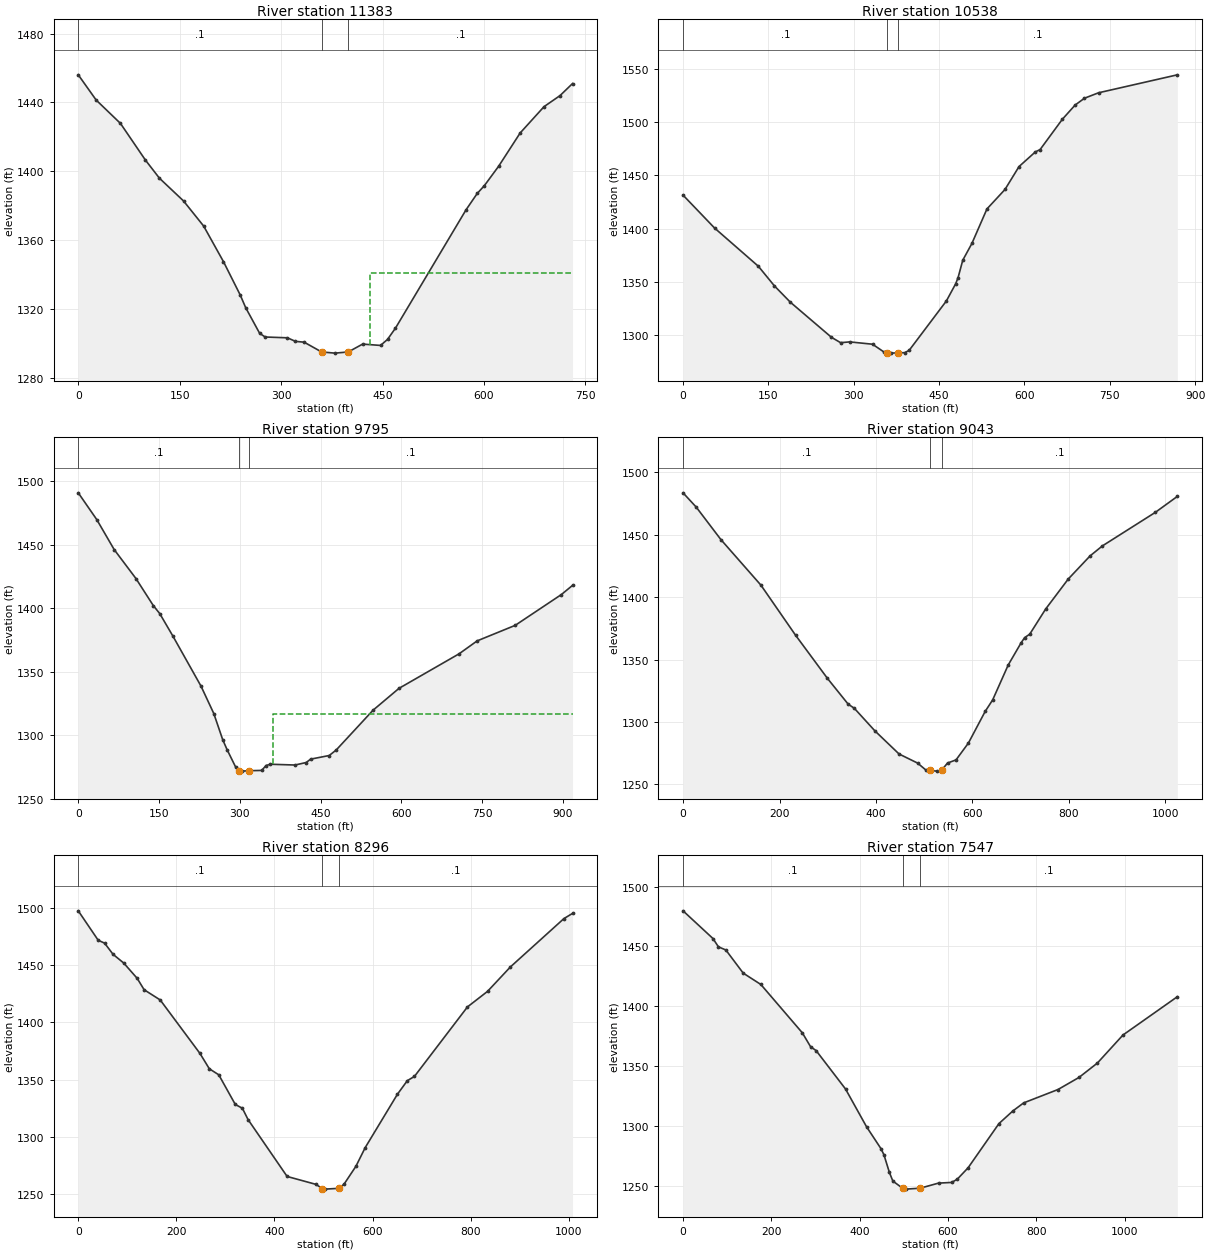
Type RM Length L Ch R = 1 ,11383   ,844.8,844.8,844.8
XS GIS Cut Line= 4
2150675.49997512 675264.53581144 2150999.6589054675185.716345517
2151072.92770471675204.5886120052151283.85303606675447.707809714
#Sta/Elev= 30
       0 1456.02    26.5 1441.36    62.4  1427.8    99.4 1406.45   120.1 1395.94
   155.7 1382.74   185.5 1368.13   214.8 1347.45   239.5 1328.14   247.7 1320.67
   268.3 1305.81   276.5 1303.68   309.4 1303.21   321.2 1301.15   334.1 1300.67
   359.9    1295   379.6 1294.31   399.3 1294.98   420.6 1299.56   447.1 1298.78
   457.4 1302.27   469.2 1308.84   573.6 1377.61   590.1 1387.08   600.7 1391.65
   621.8 1402.91   653.6 1422.23   688.9 1437.52   712.6 1443.96   731.1 1450.97
#Mann= 3 ,-1,0
       0      .1       0   359.9    .045       0   399.3      .1       0
#XS Ineff= 2 , 0
                          431.34         1341.14
Permanent Ineff=
       F       F
Bank Sta=359.9,399.3
XS Rating Curve= 0 ,0
Exp/Cntr(USF)=0,0
Exp/Cntr=0.3,0.1

Type RM Length L Ch R = 1 ,10538   ,735.4,742.8,725.4
XS GIS Cut Line= 6
2150579.87722893675342.2993111762150600.33420901 675477.67043151
2150591.30666801675572.6492441742150587.49958901675655.955508009
2150577.57375585675756.8841119262150473.39417417676196.295634672
#Sta/Elev= 30
       0 1431.51    55.5  1400.5   132.4 1364.56   160.5 1346.15   188.6 1330.75
   260.9 1297.69   276.9 1292.66   292.9  1293.4     333 1291.22   353.1 1283.88
359.24591283.093   365.2 1282.83378.14591283.094   389.4 1283.26   397.3 1285.37
   462.8 1331.93   479.2 1348.15   483.4 1353.95   491.6 1370.27   507.7 1386.09
   534.1 1418.52   565.8 1436.84   590.5 1458.41   619.3 1472.24   627.5 1474.38
   666.7 1502.96   689.1 1516.29   705.5  1522.7   730.2 1527.82   868.7 1544.72
#Mann= 3 ,-1,0
       0      .1       0359.2459    .045       0378.1459      .1       0
Bank Sta=359.2459,378.1459
XS Rating Curve= 0 ,0
Exp/Cntr(USF)=0,0
Exp/Cntr=0.3,0.1

Type RM Length L Ch R = 1 ,9795    ,762.9,752.2,734
XS GIS Cut Line= 6
2149932.79223701   675171.0352182149975.97620575675525.878012255
2149996.84919551675599.1229445042150069.99701509675797.767888427
2150105.32830925 675923.884106012150148.85512508676058.572484925
#Sta/Elev= 30
       0 1490.91    34.4 1469.82    66.7 1446.21   107.1 1423.42   139.3 1402.15
   151.4 1395.73   175.6 1378.17     228  1338.6   251.7 1317.04   268.3 1296.41
   276.3 1288.66   292.4 1274.78  299.371272.099   304.5 1271.69   316.5 1271.99
   340.7 1272.25   348.7  1276.1   356.8 1277.11   402.5  1276.5   423.3 1278.48
   431.5 1281.13     466 1283.99   478.9 1288.28   547.4 1319.67   595.6 1336.89
   707.1 1364.07   740.8  1374.3   811.4 1386.52   897.2  1410.8   917.9 1418.02
#Mann= 3 ,-1,0
       0      .1       0  299.37    .045       0   316.5      .1       0
#XS Ineff= 2 , 0
                          360.89         1316.38
Permanent Ineff=
       F       F
Bank Sta=299.37,316.5
XS Rating Curve= 0 ,0
Exp/Cntr(USF)=0,0
Exp/Cntr=0.3,0.1

Type RM Length L Ch R = 1 ,9043    ,735.8,747.3,754.6
XS GIS Cut Line= 6
 2149124.8945746675868.318600342  2149303.864361 675971.15861775
2149393.21654451676012.4846505822149552.24345742676066.625946507
2149642.69176733676109.5645089152150040.97935659676322.344923258
#Sta/Elev= 30
       0  1483.4    27.4 1471.94    78.5 1445.97   161.6 1409.45   233.3 1369.44
   299.4 1334.89   342.3  1314.3   355.1 1310.97   397.8 1292.88   447.9 1274.38
   486.3 1267.12     504 1261.38   512.8 1261.23   526.1 1260.68  536.01 1261.37
   548.3 1267.14     566 1269.68   591.7 1283.18   626.4 1308.47     642 1317.73
   674.2 1345.65   701.1 1363.49   708.2 1367.51   718.8 1370.29   751.7 1390.36
   798.6  1414.4     844 1432.96   869.6 1440.97     979 1467.72  1024.8 1480.54
#Mann= 3 ,-1,0
       0      .1       0   512.8    .045       0  536.01      .1       0
Bank Sta=512.8,536.01
XS Rating Curve= 0 ,0
Exp/Cntr(USF)=0,0
Exp/Cntr=0.3,0.1

Type RM Length L Ch R = 1 ,8296    ,731.5,749.1,765.9
XS GIS Cut Line= 6
2148786.73153701676135.6235119252148825.22325793676227.900230259
2148875.77663451676310.6274270122149073.75819393676606.799078763
2149225.54266725676815.6966268422149334.61593993676979.161851093
#Sta/Elev= 30
       0 1497.67    40.7 1471.91    53.7 1469.41      71 1459.61    92.7 1452.01
   120.2 1438.59   134.3 1428.65   167.1 1419.71   248.1 1372.96   267.3 1359.48
   286.5 1354.24   320.2  1328.3   334.7 1324.96   346.2 1315.09   425.9  1265.3
   484.6 1258.41  497.481254.741     503 1254.23   530.7  1254.9   541.6 1258.34
   566.2 1274.23   585.2 1290.62   650.9 1337.29     671  1349.1   685.5 1352.82
   793.6 1413.61   834.5  1427.2   881.1 1448.56   990.3 1490.88  1007.9 1495.43
#Mann= 3 ,-1,0
       0      .1       0  497.48    .045       0   530.7      .1       0
Bank Sta=497.48,530.7
XS Rating Curve= 0 ,0
Exp/Cntr(USF)=0,0
Exp/Cntr=0.3,0.1

Type RM Length L Ch R = 1 ,7547    ,766,750.8,696
XS GIS Cut Line= 6
2148486.91389517676032.2418289182148314.88339934676635.592984423
2148299.61112018 676732.295218842148323.35647951 676850.58992976
2148372.62180093676974.0460476732148436.76307684677098.611415342
#Sta/Elev= 30
       0 1479.74    67.7 1456.62    80.2 1449.65    96.9 1447.05   136.3  1427.7
   176.2 1418.23   270.1 1377.87   288.8 1366.25   301.3 1363.04   367.9 1330.97
   415.5 1299.42   448.3 1281.07     455 1275.92   467.3 1261.24   475.1 1254.09
     497 1248.11   504.1 1247.33   536.9  1248.1   578.6 1252.36   608.3 1252.91
     621 1255.63   645.5 1265.15   715.4 1302.09   746.9 1312.64   771.4 1319.37
   849.1 1330.52   896.5 1340.58   938.2 1352.59   996.2 1376.03  1119.3 1408.01
#Mann= 3 ,-1,0
       0      .1       0     497    .045       0   536.9      .1       0
Bank Sta=497,536.9
XS Rating Curve= 0 ,0
Exp/Cntr(USF)=0,0
Exp/Cntr=0.3,0.1

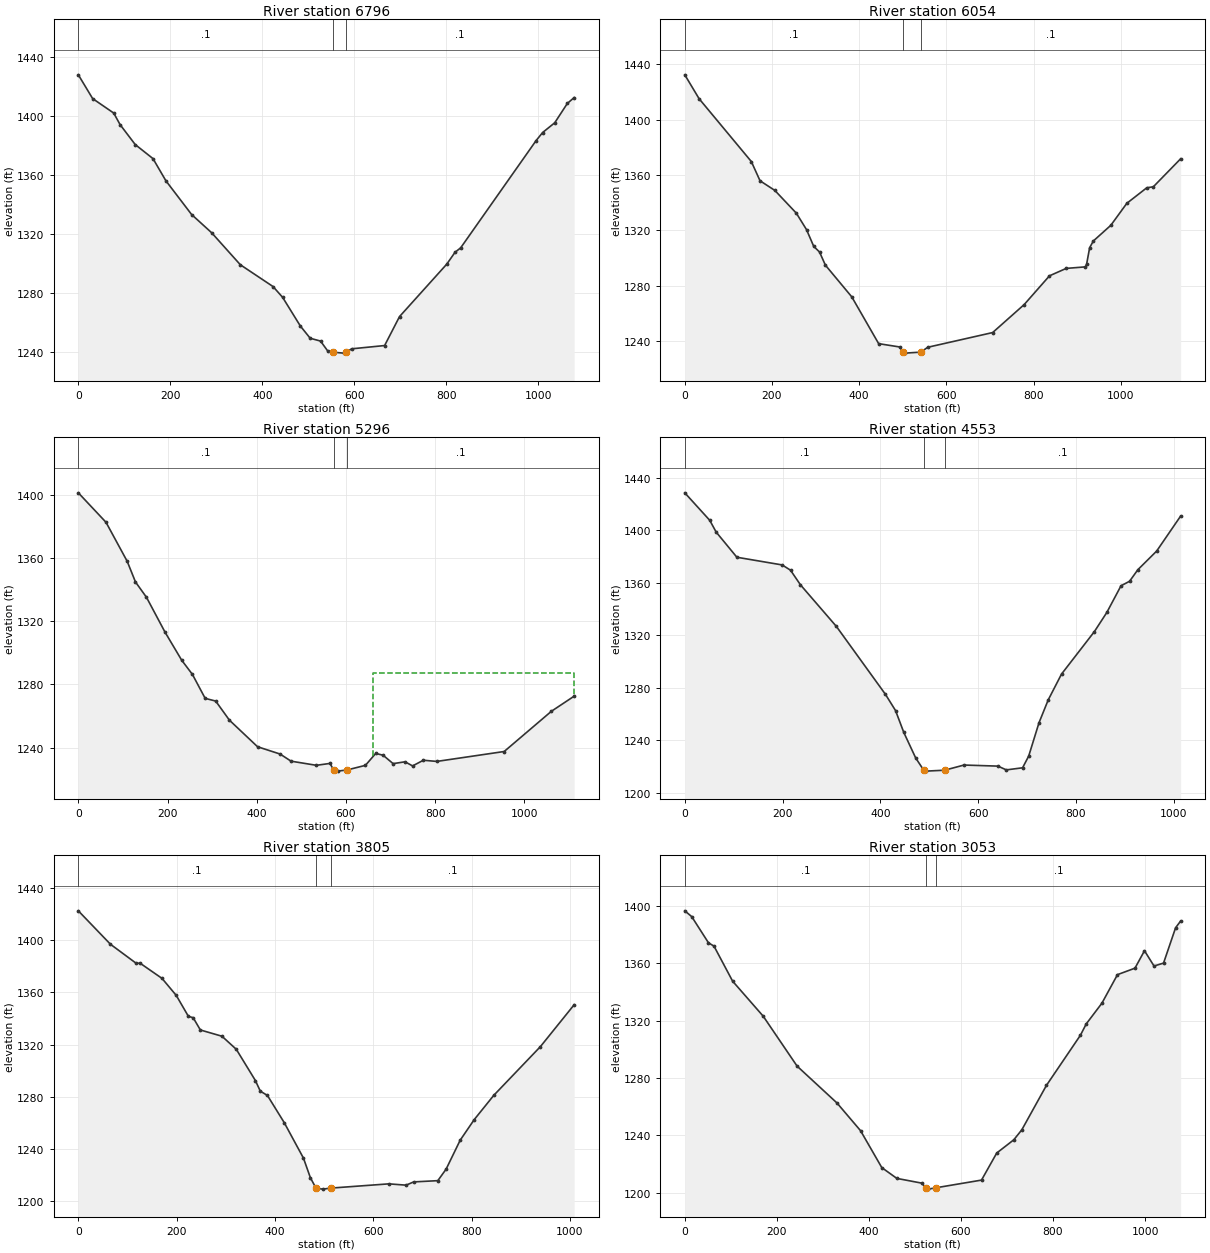
Type RM Length L Ch R = 1 ,6796    ,721.2,742.2,772.5
XS GIS Cut Line= 6
2147475.62359492676685.9042355122147644.40705001676873.919935584
2147729.75103943676924.3617638352148047.16903976 677039.08955276
 2148318.3824081677105.0313500022148409.64338042677164.103738427
#Sta/Elev= 30
       0 1427.77    31.1 1411.69    76.9  1401.9    90.8 1394.04   123.6  1380.6
   162.3 1371.05   190.3 1356.06   246.2 1333.23   289.8 1320.88     352 1299.26
   423.2 1284.47     444 1277.17   482.5 1257.78   503.9  1249.5   526.4 1247.59
   542.5 1240.66   553.5 1240.04   576.8 1239.44   582.31240.044   593.9 1242.35
   665.6 1244.57     698 1264.17   800.7 1299.68   818.6 1307.67   830.9 1310.71
   994.7 1383.22    1009 1388.73  1035.3 1395.32  1062.7 1408.42  1077.5 1412.38
#Mann= 3 ,-1,0
       0      .1       0   553.5    .045       0   582.3      .1       0
Bank Sta=553.5,582.3
XS Rating Curve= 0 ,0
Exp/Cntr(USF)=0,0
Exp/Cntr=0.3,0.1

Type RM Length L Ch R = 1 ,6054    ,750.3,757.3,742.1
XS GIS Cut Line= 6
2147417.37699226676688.3215534992147442.31919959 676791.37351276
2147362.17434676 677135.090345012147354.47882409677237.751557007
2147447.08985934677430.9978896682147659.33451359677722.567844585
#Sta/Elev= 30
       0 1432.44    32.8 1415.17   152.6 1369.75   172.6 1355.83   206.5 1348.88
   255.9 1332.41   279.2 1320.53   295.8 1308.39   309.1 1304.33   322.5 1294.85
   383.1 1271.88   444.7 1238.08   493.1 1235.67  500.521232.134   505.2 1231.23
   541.3 1231.95   557.3 1235.47   706.2  1246.1   778.5 1266.33   836.6 1287.13
     875 1292.49     919 1293.59   921.8 1295.62   928.7 1307.46   937.3 1312.34
   977.3 1323.65    1014 1339.55  1059.6 1350.74  1074.8  1351.5  1137.4 1371.73
#Mann= 3 ,-1,0
       0      .1       0  500.52    .045       0   541.3      .1       0
Bank Sta=500.52,541.3
XS Rating Curve= 0 ,0
Exp/Cntr(USF)=0,0
Exp/Cntr=0.3,0.1

Type RM Length L Ch R = 1 ,5296    ,745.4,743.7,709.9
XS GIS Cut Line= 6
2146752.32090767677180.4603330052146958.17745134677467.881018013
2146991.13506259677560.7850316762146901.58143592677897.078978509
 2146899.3553905677996.238229007 2146936.8438326678203.080335006
#Sta/Elev= 30
       0 1401.21    62.1 1382.55   109.6 1357.85   128.1 1344.82   152.8  1335.1
   194.5 1312.99   231.8 1295.27   255.9 1286.26   284.4 1271.14     308 1269.43
   338.8 1257.33   401.9 1240.52   452.4  1235.9     477 1231.39   533.8 1228.77
   564.3 1229.97   572.4 1225.85   581.7 1225.09   603.3 1225.88   643.7 1228.74
   666.9 1236.29   683.4 1235.15   705.8 1229.84   732.6 1230.99   749.5 1228.39
   773.7 1231.98   803.7 1231.23   954.9 1237.51  1060.7 1262.95  1111.8 1272.53
#Mann= 3 ,-1,0
       0      .1       0   572.4    .045       0   603.3      .1       0
#XS Ineff= 2 , 0
                          661.68          1287.5
Permanent Ineff=
       F       F
Bank Sta=572.4,603.3
XS Rating Curve= 0 ,0
Exp/Cntr(USF)=0,0
Exp/Cntr=0.3,0.1

Type RM Length L Ch R = 1 ,4553    ,755.4,747.4,739.1
XS GIS Cut Line= 6
2146163.08356909677408.8627633452146226.60279901677593.883062586
2146292.76080318677841.4534335882146333.51039359678013.912734345
2146358.55299443678100.3528501692146454.28672685 678379.26502201
#Sta/Elev= 30
       0 1428.46    51.1 1407.46    64.1 1398.55   106.5 1379.35   199.1 1373.49
   216.2 1369.48   236.5 1358.34   310.1 1326.57   410.3 1274.86     431 1262.46
   447.9 1245.77   472.2 1226.33   488.7 1216.98   492.8  1216.3  531.311216.994
     571 1220.94   640.4 1220.12   657.5 1217.24   690.8 1218.84   703.3 1227.78
   724.4  1253.2   743.3 1270.66   770.4 1290.27   837.7  1322.7   863.1 1337.28
   892.1 1357.61   909.6 1361.04   926.6 1369.88     965 1384.07    1014 1410.73
#Mann= 3 ,-1,0
       0      .1       0   488.7    .045       0  531.31      .1       0
Bank Sta=488.7,531.31
XS Rating Curve= 0 ,0
Exp/Cntr(USF)=0,0
Exp/Cntr=0.3,0.1

Type RM Length L Ch R = 1 ,3805    ,725.9,751.9,775.9
XS GIS Cut Line= 6
2145335.72564375677699.8500422542145383.18978767677786.636614084
2145584.91937108678076.4683835062145645.29228184678156.475113258
2145867.43521026678435.2567079222145922.54796092678518.367106006
#Sta/Elev= 30
       0 1422.55    65.3 1396.94   116.6 1382.64   126.4 1382.21   170.2 1370.78
   199.2 1357.72   223.9 1341.67   233.6 1340.65   248.2 1331.24   292.1 1326.46
   321.3 1316.43   360.1 1292.52   370.1 1284.39   384.7 1281.03   418.8 1260.24
   457.9 1233.04     472 1218.02   483.4 1210.01   497.3 1209.28   513.1 1210.05
   631.6 1213.32   666.7 1212.32     682 1214.81   731.2 1215.77   748.1 1224.63
   776.7 1246.79   805.2 1262.54   845.1 1281.19   939.9 1318.51  1008.5 1350.58
#Mann= 3 ,-1,0
       0      .1       0   483.4    .045       0   513.1      .1       0
Bank Sta=483.4,513.1
XS Rating Curve= 0 ,0
Exp/Cntr(USF)=0,0
Exp/Cntr=0.3,0.1

Type RM Length L Ch R = 1 ,3053    ,760.2,750,725
XS GIS Cut Line= 6
2145272.58731858677726.2991363412145224.79017009 677942.16943951
2145170.58916301678020.1715800912144928.78288808678255.631082922
2144836.50879443678432.6353220942144770.63359809 678644.99349317
#Sta/Elev= 30
       0 1396.33      15 1392.31    51.4  1374.1    63.5 1371.73   103.9 1347.38
   170.4 1322.99     244 1288.26   330.6 1262.63   381.8 1243.36     428 1217.65
   460.7 1210.14   514.5 1206.87  523.581203.676   528.6 1202.68   545.6 1203.62
   644.6 1208.96   677.7  1227.8   714.8 1237.02   732.2 1243.96   785.7 1274.88
   859.5 1309.76   872.2 1317.67   906.2 1332.06     940 1351.92     978 1356.43
   998.7 1368.56  1019.4 1357.92  1040.1 1359.96  1066.3 1384.56  1077.2 1389.22
#Mann= 3 ,-1,0
       0      .1       0  523.58    .045       0   545.6      .1       0
Bank Sta=523.58,545.6
XS Rating Curve= 0 ,0
Exp/Cntr(USF)=0,0
Exp/Cntr=0.3,0.1

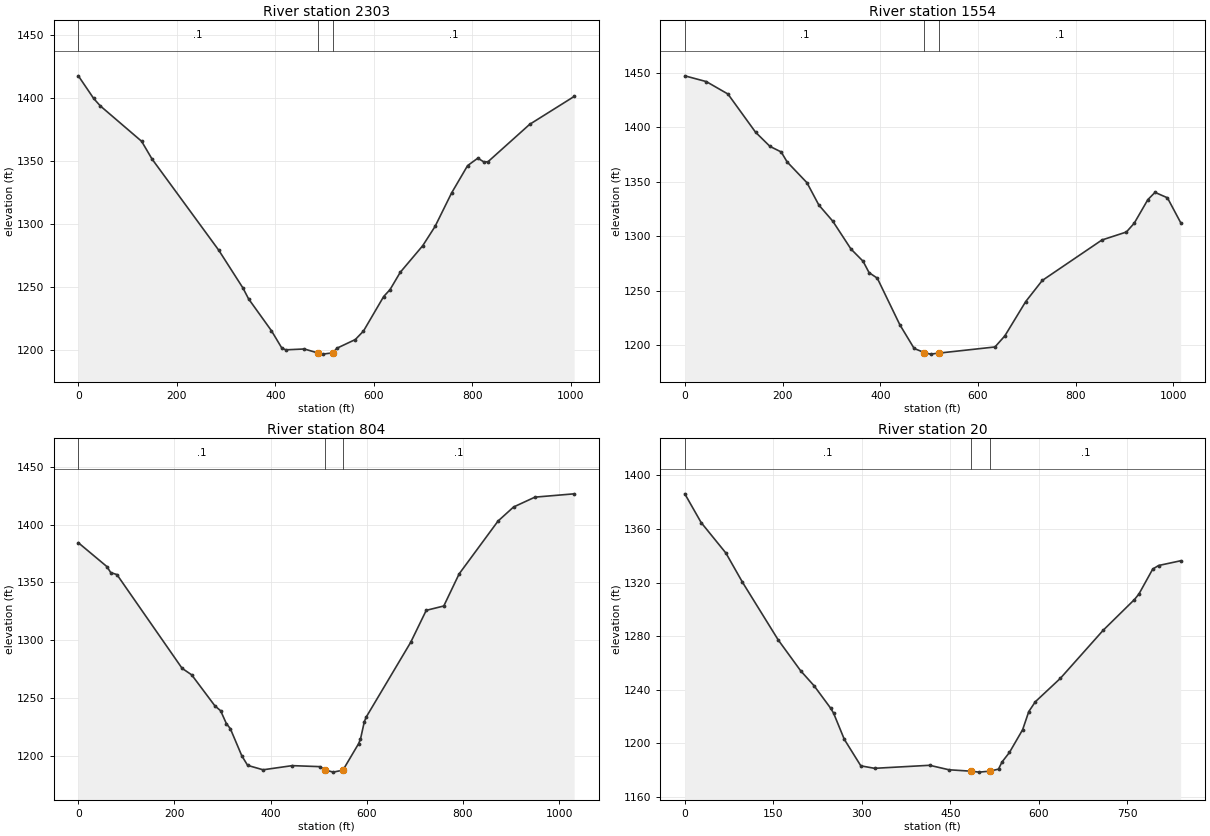
Type RM Length L Ch R = 1 ,2303    ,746.2,749.2,744.4
XS GIS Cut Line= 6
 2144195.8253645 677790.541461932144225.41749692677886.123947918
2144255.70385367677979.5876717572144285.90654917678069.121613428
2144309.50984843678153.3803031742144474.23622501678757.901403844
#Sta/Elev= 30
       0 1417.89    31.2  1399.9    44.6 1394.03   128.5 1365.94   149.5 1351.96
   285.2 1279.47   334.4 1249.44   345.7  1240.9   392.1 1215.64   413.3 1201.81
   421.5 1200.44   458.9 1201.11   486.6 1197.93   496.2 1197.03   516.9 1198.07
   525.2 1201.74   562.5 1208.61   579.1 1215.36   620.1 1242.75     633 1248.24
   653.7 1261.94   699.3 1283.04   724.4 1298.34     758 1324.93   790.5 1346.64
   811.3 1352.54   823.7 1349.53     832 1349.74   916.6  1379.4  1006.9 1401.52
#Mann= 3 ,-1,0
       0      .1       0   486.6    .045       0   516.9      .1       0
Bank Sta=486.6,516.9
XS Rating Curve= 0 ,0
Exp/Cntr(USF)=0,0
Exp/Cntr=0.3,0.1

Type RM Length L Ch R = 1 ,1554    ,739.2,749.9,760.8
XS GIS Cut Line= 6
2143509.80836384677717.4287472522143549.58453101678005.917015418
2143623.88982859 678257.730816262143637.90587668678333.071216762
2143654.13123792678517.107594088 2143652.4681835678716.216775924
#Sta/Elev= 30
       0  1447.2      44 1441.91    88.3 1430.49   144.8 1395.45   174.3 1382.43
   197.2 1377.34   209.4 1368.18     250 1349.09   274.3 1328.61   302.9 1313.75
     340 1288.25   364.8 1277.03   377.1 1266.55   393.9  1261.5   439.9 1218.84
   469.3    1197   490.4 1193.13   502.8 1191.78   520.7 1192.75   634.7 1198.36
   654.9 1208.54   697.7 1240.07   731.5 1259.39   853.6 1296.54   903.6 1303.85
   919.6  1311.9   947.6 1333.61   962.2 1340.24   987.6 1335.26  1014.6 1312.54
#Mann= 3 ,-1,0
       0      .1       0   490.4    .045       0   520.7      .1       0
Bank Sta=490.4,520.7
XS Rating Curve= 0 ,0
Exp/Cntr(USF)=0,0
Exp/Cntr=0.3,0.1

Type RM Length L Ch R = 1 ,804     ,784.4,784.4,784.4
XS GIS Cut Line= 6
2142893.14982025677869.9799513372142923.62482493678273.093646422
2142910.49263334678346.9350341712142894.61044726678445.679915428
2142862.40250643678700.2535532562142836.66797784678894.074687928
#Sta/Elev= 30
       0 1384.27    59.4 1363.63    67.4 1358.42    80.3 1356.69   215.8 1275.57
   235.8  1269.9     284 1243.12     296 1238.82     308 1227.66   316.1  1223.4
   340.1 1199.79   352.2 1191.55   384.3 1187.72     445 1191.32   501.8 1190.46
     514 1187.54   530.2  1185.7   550.4  1187.4   582.8 1210.19   586.8 1214.06
   594.9 1229.35   598.9 1233.41   691.5 1298.18   723.7 1325.74   760.2 1329.51
   792.1 1357.28   873.1 1403.05   905.4 1415.21   949.8 1423.73  1031.4  1426.6
#Mann= 3 ,-1,0
       0      .1       0     514    .045       0   550.4      .1       0
Bank Sta=514,550.4
XS Rating Curve= 0 ,0
Exp/Cntr(USF)=0,0
Exp/Cntr=0.3,0.1

Type RM Length L Ch R = 1 ,20      ,,,
XS GIS Cut Line= 2
2141840.43311409678243.4042208582142560.72537982678675.884143623
#Sta/Elev= 30
       0 1386.12    27.7 1364.71    69.7 1341.94    97.7 1320.24   158.3  1277.2
   196.4 1254.16     219 1243.08     247 1226.41   252.1 1222.64   270.3  1203.1
   298.3 1183.33   321.6 1181.49   414.9 1183.75   447.6 1180.41   484.5 1179.36
   498.9 1178.65   517.6 1179.42   531.6 1180.91   537.5 1186.18   550.2 1193.37
   572.5 1210.31   582.9 1223.81     594 1231.12   636.3 1248.52   708.9 1284.38
     762 1307.33   769.5 1311.41   792.9 1330.01   802.8 1332.68   840.2 1336.21
#Mann= 3 ,-1,0
       0      .1       0   484.5    .045       0   517.6      .1       0
Bank Sta=484.5,517.6
XS Rating Curve= 0 ,0
Exp/Cntr(USF)=0,0
Exp/Cntr=0.3,0.1
LCMann Table=0

Chan Stop Cuts=-1
Use User Specified Reach Order=0
Composite Channel Slope=5